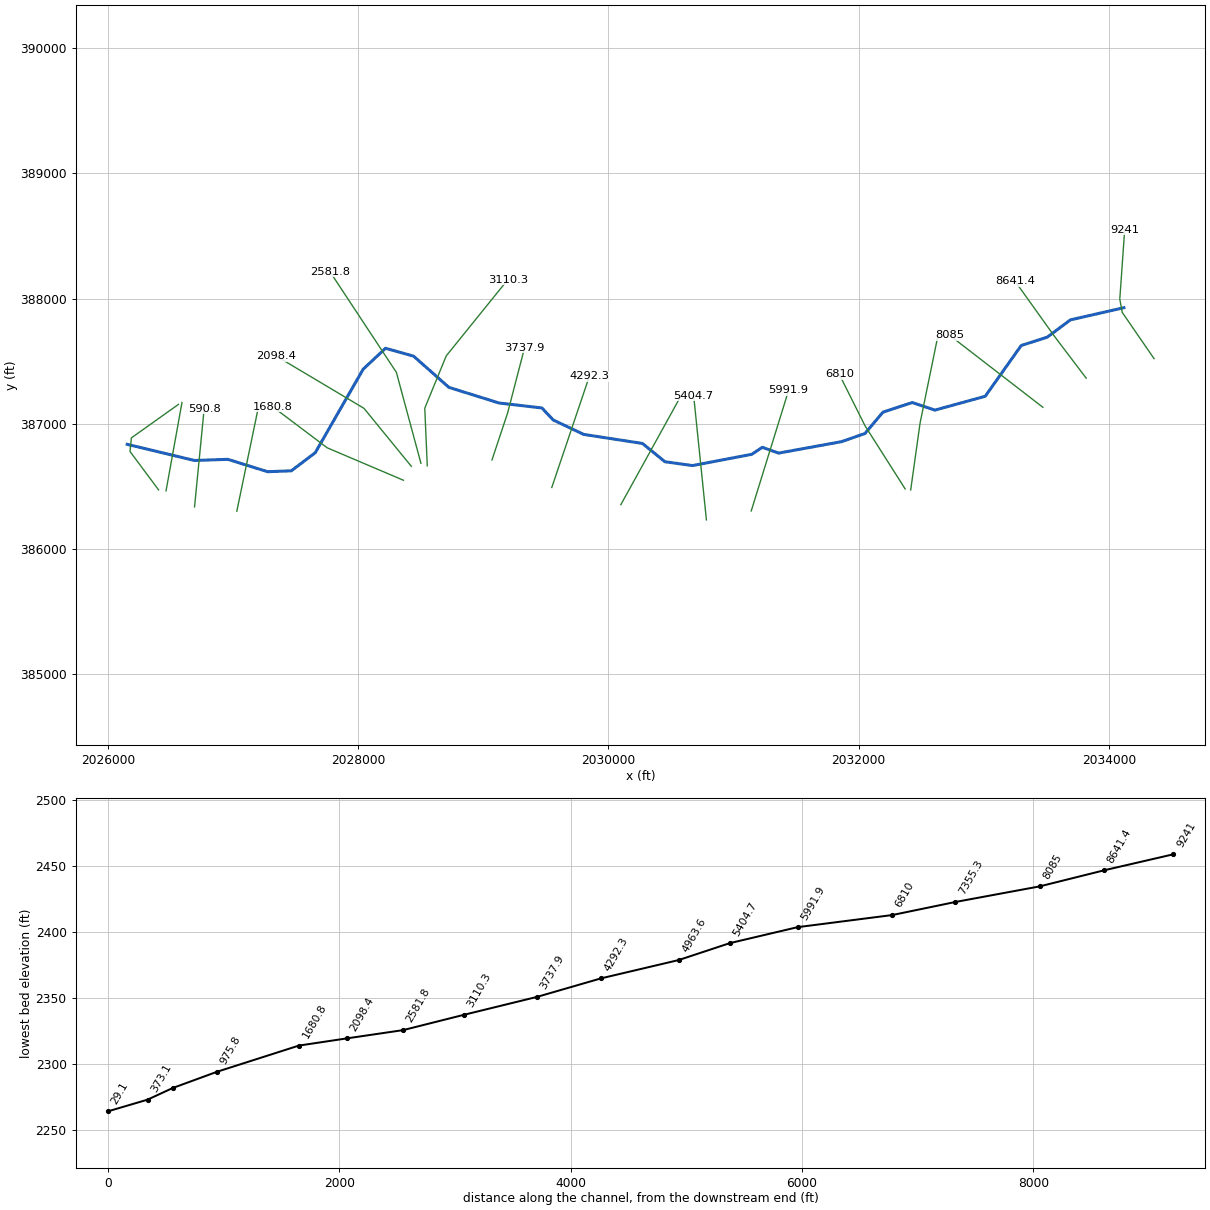
--- BurdetteCk.prj (project) ---

Proj Title=BurdetteCk
Current Plan=p01
Default Exp/Contr=0,0
English Units
Geom File=g01
Flow File=f01
Plan File=p01
BEGIN DESCRIPTION:
END DESCRIPTION:
DSS Export Rating Curves= 0
DSS Export Rating Curve Sorted= 0
DSS Export Volume Flow Curves= 0
DXF OffsetX= 0
DXF OffsetY= 0
DXF ScaleX= 0
DXF ScaleY= 0

--- BurdetteCk.p01 (plan) ---

Plan Title=Floodplain
Program Version=4.00
Geom File=g01
Flow File=f01
K Sum by GR=0
Std Step Tol=0.01
Critical Tol=0.01
Num of Std Step Trials=20
Max Error Tol=0.3
Flow Tol Ratio=0.001
Split Flow NTrial=30
Split Flow Tol=0.02
Split Flow Ratio=0.02
Log Output Level=0
Friction Slope Method=1
Unsteady Friction Slope Method=2
Unsteady Bridges Friction Slope Method=1
Global Log Level=0
CheckData=False
Run HTab=0
Run UNet=0
Run PostProcess=0
UNET Theta=0
UNET Theta Warmup=0
UNET ZTol=0
UNET ZSATol=0
UNET MxIter=0
UNET MaxInSteps=0
UNET DtIC=0
UNET DtMin=0
UNET MaxCRTS=0
UNET WFStab=0
UNET SFStab=0
UNET WFX=0
UNET SFX=0
UNET DSS MLevel=0
UNET DZMax Abort=0
UNET Convert EG Bridges=0
UNET Use Existing IB Tables=0
UNET Froude Limit=0
UNET Froude Power=0
Write IC File=0
Echo Input=False
Echo Output=False
Write Detailed=0

--- BurdetteCk.f01 (steady flow) ---

Flow Title=Moglen and others (2006)
Program Version=4.00
Number of Profiles=1
Profile Names=P100yr
River Rch & RM=BurdetteCk,Main      ,9241
519.1744
River Rch & RM=BurdetteCk,Main      ,7355.3
551.9811
River Rch & RM=BurdetteCk,Main      ,6810
781.2541
River Rch & RM=BurdetteCk,Main      ,2581.8
845.8977
River Rch & RM=BurdetteCk,Main      ,2098.4
1166.639
River Rch & RM=BurdetteCk,Main      ,29.1
1200.273
Boundary for River Rch & Prof#=BurdetteCk,Main      ,1
Up Type=0
Dn Type=3
Dn Slope=0.032777

--- BurdetteCk.g01 (geometry) ---

Geom Title=USGS 10m DEM
Program Version=4.10

River Reach=BurdetteCk      ,Main
Reach XY= 30
     2034120.713      387927.611     2033692.891      387830.103
     2033507.574      387691.788     2033299.621      387625.329
     2033012.227       387219.69     2032610.204      387109.296
     2032429.221      387169.763     2032194.471      387092.585
     2032050.833      386922.149     2031862.175      386856.762
     2031361.419      386765.725     2031229.742      386811.742
     2031146.132      386756.001     2030672.703      386665.949
     2030451.916      386696.647     2030272.579      386842.528
     2029802.289      386915.106     2029558.618      387030.413
     2029468.406      387126.416     2029126.008      387165.969
     2028725.201      387290.812     2028442.983      387540.245
     2028218.359      387603.355     2028039.706      387436.135
     2027656.673      386768.686     2027465.377      386624.035
     2027275.878      386616.951      2026957.78      386715.804
     2026690.849      386706.683     2026153.013      386835.878

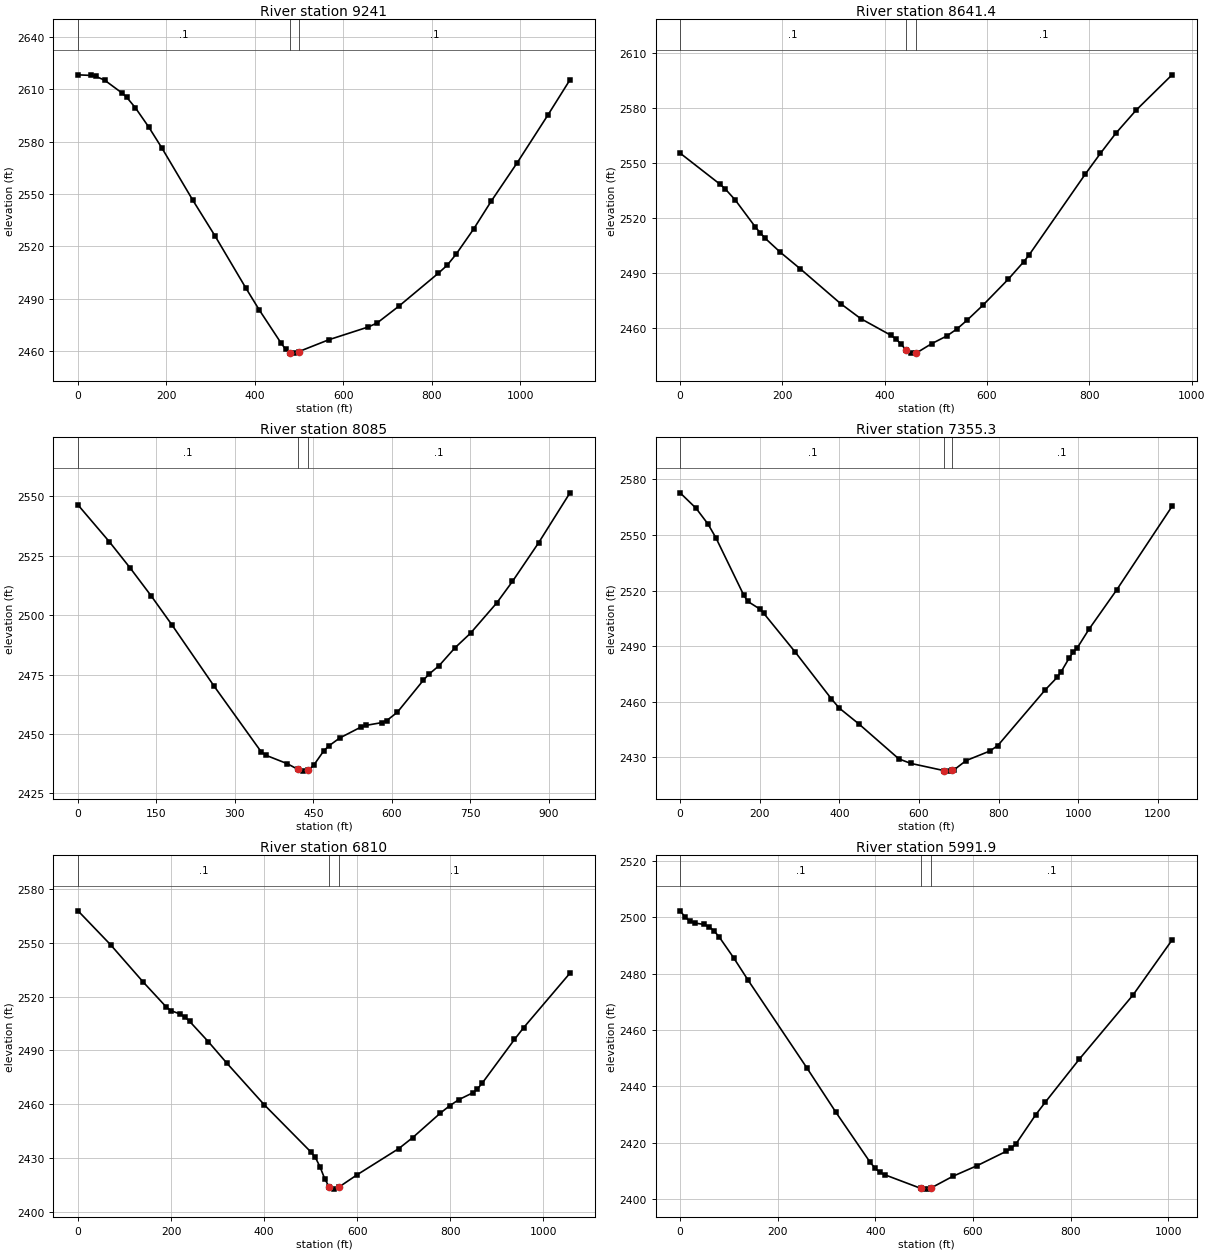
Type RM Length L Ch R = 1 ,9241    ,586.2,599.6,613
XS GIS Cut Line= 4
     2034361.807      387520.305     2034106.747      387890.748
     2034087.849      387996.612      2034126.99      388550.664
#Sta/Elev= 30
       0  2618.3      30 2617.95      40 2617.41      60 2615.28     100 2607.78
   109.9 2605.49   129.9 2599.35   159.9 2588.38   189.9 2576.25   259.9 2546.28
   309.8 2525.93   379.8 2495.92   409.8 2483.51   459.5 2464.34   469.3 2460.95
   478.9    2459   488.9 2458.67   498.9 2459.49   567.2 2466.34   656.5 2473.67
   676.3 2475.92   725.9 2485.64   815.2 2504.54     835  2509.1   854.8 2515.28
   894.5 2529.74   934.2 2545.68   993.7 2568.01  1063.1 2595.37  1112.7 2615.44
#Mann= 3 , 0 , 0
       0      .1       0   478.9    .045       0   498.9      .1       0
Bank Sta=478.9,498.9
XS Rating Curve= 0 ,0
Exp/Cntr=0.3,0.1

Type RM Length L Ch R = 1 ,8641.4  ,547.2,556.3,565.5
XS GIS Cut Line= 3
       2033819.3      387364.435     2033570.313      387692.369
     2033250.477      388139.735
#Sta/Elev= 30
       0 2555.54    78.4 2538.51    88.2 2536.04   107.8    2530     147 2515.33
   156.9    2512   166.7 2509.02   196.1 2501.47   235.3  2492.4   313.7 2473.54
   352.9 2465.38   411.8 2456.31   421.7 2454.31   431.7 2451.52   441.7 2448.24
   451.7 2446.54   461.7 2446.59   491.7 2451.69   521.7 2455.94   541.7 2459.82
   561.7 2464.67   591.7 2472.58   641.7 2486.88   671.7 2496.33   681.7 2499.84
   791.7 2543.96   821.7 2555.43   851.7 2566.35   891.7 2579.04   961.7 2598.22
#Mann= 3 , 0 , 0
       0      .1       0   441.7    .045       0   461.7      .1       0
Bank Sta=441.7,461.7
XS Rating Curve= 0 ,0
Exp/Cntr=0.3,0.1

Type RM Length L Ch R = 1 ,8085    ,763.6,729.7,695.7
XS GIS Cut Line= 2
     2033473.148      387131.643     2032728.212      387706.539
#Sta/Elev= 30
       0 2546.25    60.1 2530.75   100.1 2519.67   140.2 2507.97   180.2 2495.68
   260.3 2470.11   350.4 2442.51   360.4 2440.98   400.4 2437.51   420.4 2435.16
   430.4  2434.4   440.4 2434.83   450.5 2436.78   470.5 2443.05   480.5 2445.12
   500.5 2448.31   540.6 2452.86   550.6 2453.62   580.6 2454.77   590.6 2455.66
   610.6  2459.1   660.7 2472.64   670.7 2475.03   690.7 2478.73   720.8 2486.17
   750.8 2492.37   800.8 2505.05   830.9 2514.09   880.9 2530.32     941 2551.35
#Mann= 3 , 0 , 0
       0      .1       0   420.4    .045       0   440.4      .1       0
Bank Sta=420.4,440.4
XS Rating Curve= 0 ,0
Exp/Cntr=0.3,0.1

Type RM Length L Ch R = 1 ,7355.3  ,521,545.3,569
XS GIS Cut Line= 3
     2032416.473      386471.727     2032491.371      387006.137
     2032631.047       387688.32
#Sta/Elev= 30
       0 2572.69      40 2564.39      70 2555.87    89.9 2548.45   159.9 2517.51
   169.9 2514.15   199.9 2510.06   209.9 2507.76   289.8 2486.64   379.7 2461.67
   399.7 2456.61   449.7 2447.93   549.6 2429.17   579.4 2426.76  664.032422.807
   678.9 2422.58   683.6 2422.96   688.8 2423.38   718.7 2428.28   778.4 2433.44
   798.3  2436.4   917.6 2466.48   947.5 2473.21   957.4 2476.21   977.3 2483.51
   987.3 2486.67   997.2 2488.84  1027.1 2499.07  1096.7 2520.28    1236 2565.42
#Mann= 3 , 0 , 0
       0      .1       0  664.03    .045       0   683.6      .1       0
Bank Sta=664.03,683.6
XS Rating Curve= 0 ,0
Exp/Cntr=0.3,0.1

Type RM Length L Ch R = 1 ,6810    ,845.1,818.1,791.4
XS GIS Cut Line= 3
     2032371.939      386479.824     2032050.078      386985.895
     2031845.626      387394.799
#Sta/Elev= 30
       0 2567.74      70 2548.83   139.9 2528.11   189.9 2514.08   199.9 2512.12
   219.9 2510.19   229.9 2508.59   239.9 2506.13   279.9 2494.86   319.9 2482.84
   399.8 2459.79   499.8 2433.53   509.8  2430.4   519.8 2425.19   529.8 2418.61
   539.8 2413.78   549.8 2412.71   559.8 2413.72   599.8 2420.74   689.2 2435.31
     719 2441.41   778.6  2455.1   798.5 2459.16   818.4  2462.6   848.2 2466.37
   858.2 2468.53   868.1 2471.66   937.7  2496.1   957.5 2502.71  1056.9 2533.03
#Mann= 3 , 0 , 0
       0      .1       0   539.8    .045       0   559.8      .1       0
Bank Sta=539.8,559.8
XS Rating Curve= 0 ,0
Exp/Cntr=0.3,0.1

Type RM Length L Ch R = 1 ,5991.9  ,574.7,587.2,599.3
XS GIS Cut Line= 2
     2031141.753      386303.753     2031440.276      387266.491
#Sta/Elev= 30
       0 2502.32      10 2500.17      20 2498.67    29.9 2497.99    49.9 2497.47
    59.9 2496.61    69.9 2495.11    79.8 2493.12   109.8 2485.63   139.7  2477.6
   259.5 2446.64   319.4 2430.78   389.2 2413.12   399.2 2411.01   409.2 2409.53
   419.2 2408.66  492.852403.839     499 2403.55     509 2403.61  513.69 2403.92
   558.9 2408.11   608.8  2411.9   668.6    2417   678.6 2418.04   688.6 2419.72
   728.5 2429.92   748.5 2434.46   818.3 2449.75   928.1 2472.47    1008 2491.96
#Mann= 3 , 0 , 0
       0      .1       0  492.85    .045       0  513.69      .1       0
Bank Sta=492.85,513.69
XS Rating Curve= 0 ,0
Exp/Cntr=0.3,0.1

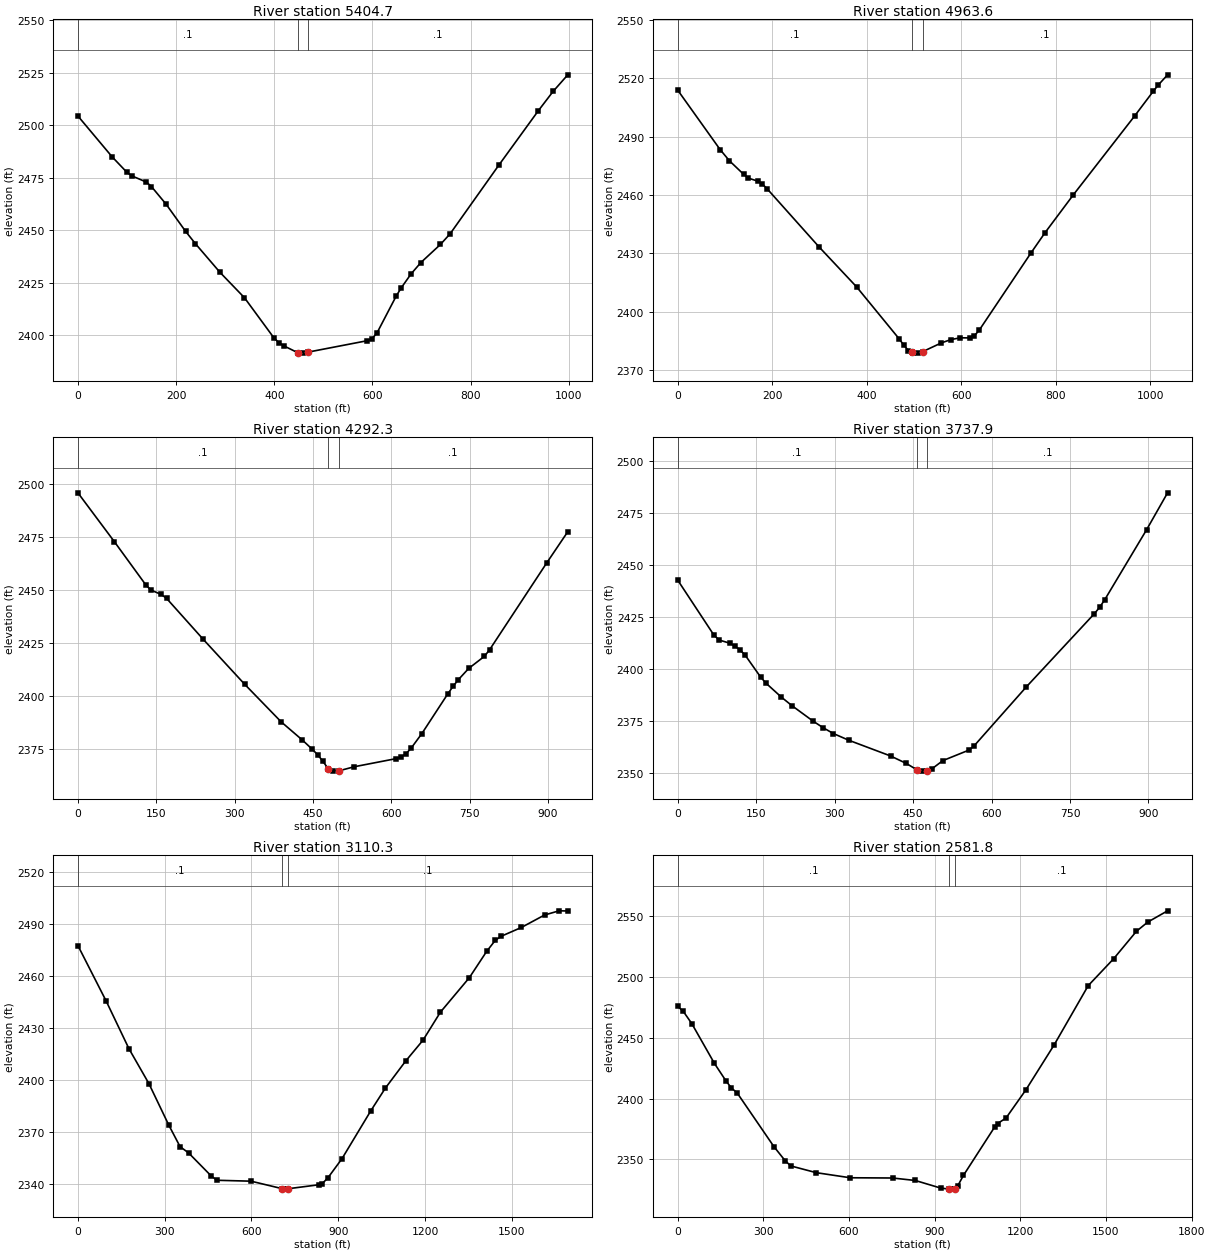
Type RM Length L Ch R = 1 ,5404.7  ,459.1,441.1,423.4
XS GIS Cut Line= 2
     2030783.525       386231.61     2030681.529        387224.2
#Sta/Elev= 30
       0 2504.33    69.8 2484.87    99.8 2477.52   109.8 2475.83   139.7 2472.85
   149.7 2470.75   179.6 2462.35   219.5 2449.36   239.5 2443.49   289.4 2429.89
   339.3 2417.79   399.1 2398.73   409.1 2396.45   419.1 2394.93     449  2391.5
     459 2391.43     469 2391.92   588.7 2397.32   598.7 2398.29   608.7 2400.82
   648.6 2418.72   658.6 2422.52   678.5 2429.12   698.5 2434.54   738.4 2443.17
   758.3 2448.29   858.1 2481.17     938 2506.91   967.9 2516.04   997.8 2523.94
#Mann= 3 , 0 , 0
       0      .1       0     449    .045       0     469      .1       0
Bank Sta=449,469
XS Rating Curve= 0 ,0
Exp/Cntr=0.3,0.1

Type RM Length L Ch R = 1 ,4963.6  ,666.1,671.3,676.6
XS GIS Cut Line= 2
     2030099.409      386353.507     2030600.666      387260.693
#Sta/Elev= 30
       0 2513.83    89.7  2483.3   109.6 2477.48   139.5 2470.56   149.5 2468.62
   169.4 2467.05   179.4  2465.5   189.4 2463.08     299 2433.27   378.7 2412.66
   468.4 2386.05   478.4 2382.75   488.3 2379.95  495.352379.069   498.3  2378.7
   508.3 2378.66   518.3 2379.42   558.1 2383.94     578 2385.61     598 2386.54
   617.9 2386.48   627.8 2387.59   637.8 2390.39   747.4 2430.12   777.3 2440.59
   837.1 2460.02   966.7 2500.51  1006.6 2513.36  1016.5 2516.39  1036.5  2521.7
#Mann= 3 , 0 , 0
       0      .1       0  495.35    .045       0   518.3      .1       0
Bank Sta=495.35,518.3
XS Rating Curve= 0 ,0
Exp/Cntr=0.3,0.1

Type RM Length L Ch R = 1 ,4292.3  ,551.8,554.4,556.2
XS GIS Cut Line= 2
     2029547.458      386491.043     2029847.937      387379.829
#Sta/Elev= 30
       0 2495.75    69.9 2472.74   129.8 2452.51   139.7 2450.01   159.7 2447.92
   169.7 2446.12   239.5 2426.96   319.4 2405.67   389.3 2387.99   429.2 2379.58
   449.1 2375.04   459.1 2372.53   469.1 2369.47   479.1 2366.04   489.1 2364.81
   499.1  2364.9     529 2366.86   608.8 2370.66   618.8 2371.39   628.8 2373.06
   638.8 2375.82   658.7 2382.46   708.6 2401.23   718.6 2404.72   728.6 2407.84
   748.6 2413.16   778.5 2418.82   788.5 2421.93   898.3 2462.94   938.2 2477.45
#Mann= 3 , 0 , 0
       0      .1       0   479.1    .045       0   499.1      .1       0
Bank Sta=479.1,499.1
XS Rating Curve= 0 ,0
Exp/Cntr=0.3,0.1

Type RM Length L Ch R = 1 ,3737.9  ,631.5,627.6,624.1
XS GIS Cut Line= 3
     2029069.198      386710.719     2029194.703      387087.235
      2029330.33        387609.5
#Sta/Elev= 30
       0  2442.7    69.4 2416.17    79.4 2413.85    99.2 2412.37   109.1 2411.01
   119.1 2409.15     129 2406.57   158.8 2395.95   168.7 2393.12   198.4 2386.34
   218.3  2382.3     258 2374.98   277.8 2371.69   297.7 2368.85   327.4  2365.6
   406.9 2358.07   436.8  2354.5   456.8  2351.5   466.8 2350.77   476.8 2350.79
   486.8 2352.02   506.8 2355.82   556.8 2360.89   566.8 2362.97   666.7 2391.37
   796.6 2426.55   806.6 2429.61   816.6 2433.36   896.5 2466.99   936.5 2484.71
#Mann= 3 , 0 , 0
       0      .1       0   456.8    .045       0   476.8      .1       0
Bank Sta=456.8,476.8
XS Rating Curve= 0 ,0
Exp/Cntr=0.3,0.1

Type RM Length L Ch R = 1 ,3110.3  ,497.6,528.4,559.2
XS GIS Cut Line= 4
      2028552.12      386664.034     2028532.161      387124.692
     2028703.812      387542.625     2029194.703      388149.983
#Sta/Elev= 30
       0 2477.65    98.1 2445.56   176.6 2418.18   245.3 2398.18   313.9 2374.32
   353.2  2361.8   382.6  2358.2   461.1 2344.88   480.7 2342.42   598.6  2341.9
   706.5 2337.58   716.5 2337.32   726.5 2337.54   834.3 2339.86   844.2 2340.42
   863.8  2343.7   912.9 2354.81    1013 2382.52  1063.1 2395.53  1133.2 2411.11
  1193.2 2423.12  1253.3 2439.26  1353.4 2459.14  1413.5 2474.35  1443.5 2480.74
  1463.6 2483.02  1533.6  2488.1  1613.7 2495.28  1663.8 2497.67  1693.8 2497.59
#Mann= 3 , 0 , 0
       0      .1       0   706.5    .045       0   726.5      .1       0
Bank Sta=706.5,726.5
XS Rating Curve= 0 ,0
Exp/Cntr=0.3,0.1

Type RM Length L Ch R = 1 ,2581.8  ,469.7,483.4,497.1
XS GIS Cut Line= 3
     2028501.513      386684.277     2028305.158      387410.994
     2027774.797      388214.633
#Sta/Elev= 30
       0 2475.68    19.8  2471.5    49.5 2461.49   128.8 2428.81   168.4 2414.75
   188.2 2408.66     208 2404.72   336.8 2360.63   376.4 2348.97   396.2 2344.72
   485.3 2339.18   604.2 2335.01   752.8 2334.81   832.2 2332.77   921.5 2326.51
   951.2 2325.74   961.2 2325.68   971.2 2326.04   981.1  2328.5  1000.9 2337.02
  1110.1 2376.68  1120.1 2379.49  1149.8 2384.02  1219.3 2407.12  1318.6 2444.15
  1437.7  2492.7    1527 2514.83  1606.5 2537.29  1646.2 2544.86  1715.6  2554.1
#Mann= 3 , 0 , 0
       0      .1       0   951.2    .045       0   971.2      .1       0
Bank Sta=951.2,971.2
XS Rating Curve= 0 ,0
Exp/Cntr=0.3,0.1

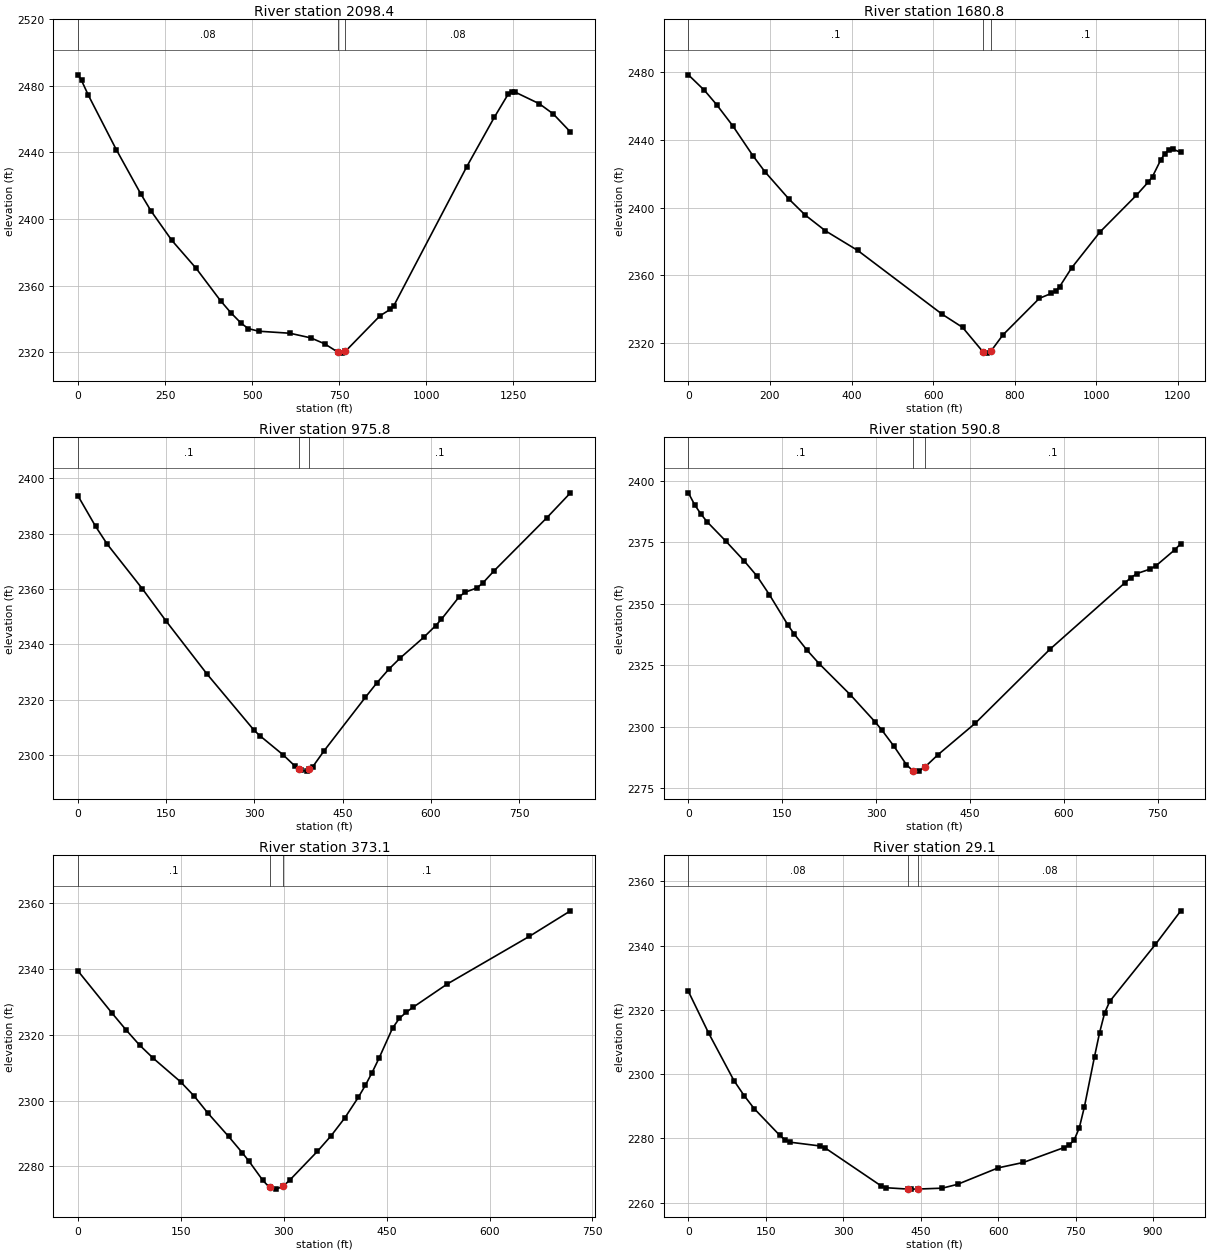
Type RM Length L Ch R = 1 ,2098.4  ,420.9,417.6,414.3
XS GIS Cut Line= 3
     2028424.591      386659.985      2028046.05      387123.546
     2027345.649      387540.548
#Sta/Elev= 30
       0 2486.62      10 2483.25    29.9 2474.24   109.7 2441.74   179.5 2415.34
   209.5 2404.85   269.3 2387.18   339.1 2370.38     409 2350.96   438.9 2343.67
   468.8 2337.32   488.8  2334.2   518.7 2332.63   608.4 2331.41   668.1 2328.63
   707.8 2325.08   747.5 2319.85   757.5 2319.47   767.5 2320.56   866.9  2341.9
   896.7 2345.81   906.6 2347.99  1115.4 2431.27  1194.9 2461.08  1234.7 2474.99
  1244.6 2476.57  1254.6 2476.25  1324.2 2469.25  1363.9 2463.19  1413.6 2452.27
#Mann= 3 , 0 , 0
       0     .08       0   747.5    .045       0   767.5     .08       0
Bank Sta=747.5,767.5
XS Rating Curve= 0 ,0
Exp/Cntr=0.3,0.1

Type RM Length L Ch R = 1 ,1680.8  ,738.9,705,670.5
XS GIS Cut Line= 3
     2028361.838       386548.65     2027752.529      386807.758
     2027317.309      387135.691
#Sta/Elev= 30
       0 2478.55    39.5 2469.35    69.2 2460.94   108.7 2448.44   158.1 2430.77
   187.8  2421.2   247.1 2404.94   286.6 2395.59     336  2386.3   415.1  2374.7
   622.6 2336.89     672 2329.23   721.5 2314.93   731.5 2313.98   741.5 2315.11
   771.1 2324.77   860.3 2346.37     890 2349.33   899.9 2350.71   909.8 2353.21
   939.5 2364.41  1008.9 2385.61  1098.1 2407.31  1127.8 2415.29  1137.7 2418.42
  1157.5 2428.07  1167.4 2431.82  1177.3 2434.19  1187.2 2434.61    1207  2432.7
#Mann= 3 , 0 , 0
       0      .1       0   721.5    .045       0   741.5      .1       0
Bank Sta=721.5,741.5
XS Rating Curve= 0 ,0
Exp/Cntr=0.3,0.1

Type RM Length L Ch R = 1 ,975.8   ,382,385,388.5
XS GIS Cut Line= 2
     2027029.861      386301.688     2027199.901      387121.521
#Sta/Elev= 30
       0 2393.65    29.9 2382.64    49.8 2376.18   109.6 2360.05   149.5 2348.52
   219.3 2329.32     299 2309.09     309 2307.07   348.9  2300.1   368.8 2296.08
  375.262295.062   378.7 2294.52   388.7 2294.25   393.32294.926   398.7 2295.72
   418.6 2301.66   488.4 2320.86   508.4 2326.21   528.3 2331.04   548.2 2335.19
   588.1 2342.64     608 2346.79     618 2349.15   647.9 2357.19   657.9 2358.85
   677.8 2360.39   687.8  2362.1   707.7 2366.67   797.4 2385.84   837.3 2394.78
#Mann= 3 , 0 , 0
       0      .1       0  375.26    .045       0   393.3      .1       0
Bank Sta=375.26,393.3
XS Rating Curve= 0 ,0
Exp/Cntr=0.3,0.1

Type RM Length L Ch R = 1 ,590.8   ,220,217.6,215.2
XS GIS Cut Line= 2
     2026691.806        386336.1     2026768.729      387119.497
#Sta/Elev= 30
       0 2395.19      10 2390.36    19.9 2386.62    29.9 2383.41    59.8 2375.56
    89.7 2367.34   109.6 2361.34   129.5 2353.75   159.4 2341.28   169.4 2337.65
   189.3 2331.27   209.2 2325.62   259.1 2312.95   298.9 2301.84   308.9 2298.76
   328.8 2291.99   348.7 2284.49   358.7 2282.11   368.7 2281.91   378.7  2283.7
   398.6 2288.49   458.4 2301.35   577.9 2331.49   697.5 2358.49   707.4 2360.66
   717.4 2362.35   737.3 2364.07   747.3 2365.45   777.2 2371.92   787.2 2374.49
#Mann= 3 , 0 , 0
       0      .1       0   358.7    .045       0   378.7      .1       0
Bank Sta=358.7,378.7
XS Rating Curve= 0 ,0
Exp/Cntr=0.3,0.1

Type RM Length L Ch R = 1 ,373.1   ,341.7,344.1,346.5
XS GIS Cut Line= 2
     2026463.948      386463.757     2026591.478      387170.231
#Sta/Elev= 30
       0 2339.44    49.8 2326.57    69.8 2321.58    89.7 2316.91   109.7  2312.9
   149.6 2305.72   169.5 2301.36   189.4  2296.2   219.4 2289.14   239.3  2284.2
   249.3 2281.57   269.2 2275.82   279.2  2273.6   289.2  2273.1   299.2 2274.02
   309.1 2275.94     349  2284.6   368.9 2289.32   388.9 2294.76   408.8 2301.08
   418.8 2304.65   428.7 2308.56   438.7 2312.88   458.6 2322.11   468.6 2325.08
   478.6 2326.92   488.6 2328.44   538.4 2335.51   658.1    2350   717.9 2357.75
#Mann= 3 , 0 , 0
       0      .1       0   279.2    .045       0   299.2      .1       0
Bank Sta=279.2,299.2
XS Rating Curve= 0 ,0
Exp/Cntr=0.3,0.1

Type RM Length L Ch R = 1 ,29.1    ,34.6,29.1,23.5
XS GIS Cut Line= 4
     2026404.358      386471.727     2026175.961      386778.542
     2026186.934      386887.179     2026563.323      387154.931
#Sta/Elev= 30
       0 2325.76    39.2 2312.78    88.3 2297.99   107.9 2293.34   127.5 2289.26
   176.5 2281.04   186.3 2279.66   196.2 2278.84     255 2277.65   264.8 2277.04
   372.7 2265.29   382.5 2264.66   425.62264.226   432.1 2264.22   444.5 2264.24
   491.7 2264.52   521.2 2265.71   599.8 2270.83   648.9 2272.53   727.6 2277.16
   737.4  2277.9   747.2 2279.54     757 2283.26   766.9  2289.8   786.5 2305.44
   796.4 2312.94   806.2 2319.09     816 2322.64   904.4 2340.34   953.6 2350.81
#Mann= 3 , 0 , 0
       0     .08       0   425.6    .045       0   444.5     .08       0
Bank Sta=425.6,444.5
XS Rating Curve= 0 ,0
Exp/Cntr=0.3,0.1

Chan Stop Cuts=-1
Use User Specified Reach Order=0
Composite Channel Slope=5